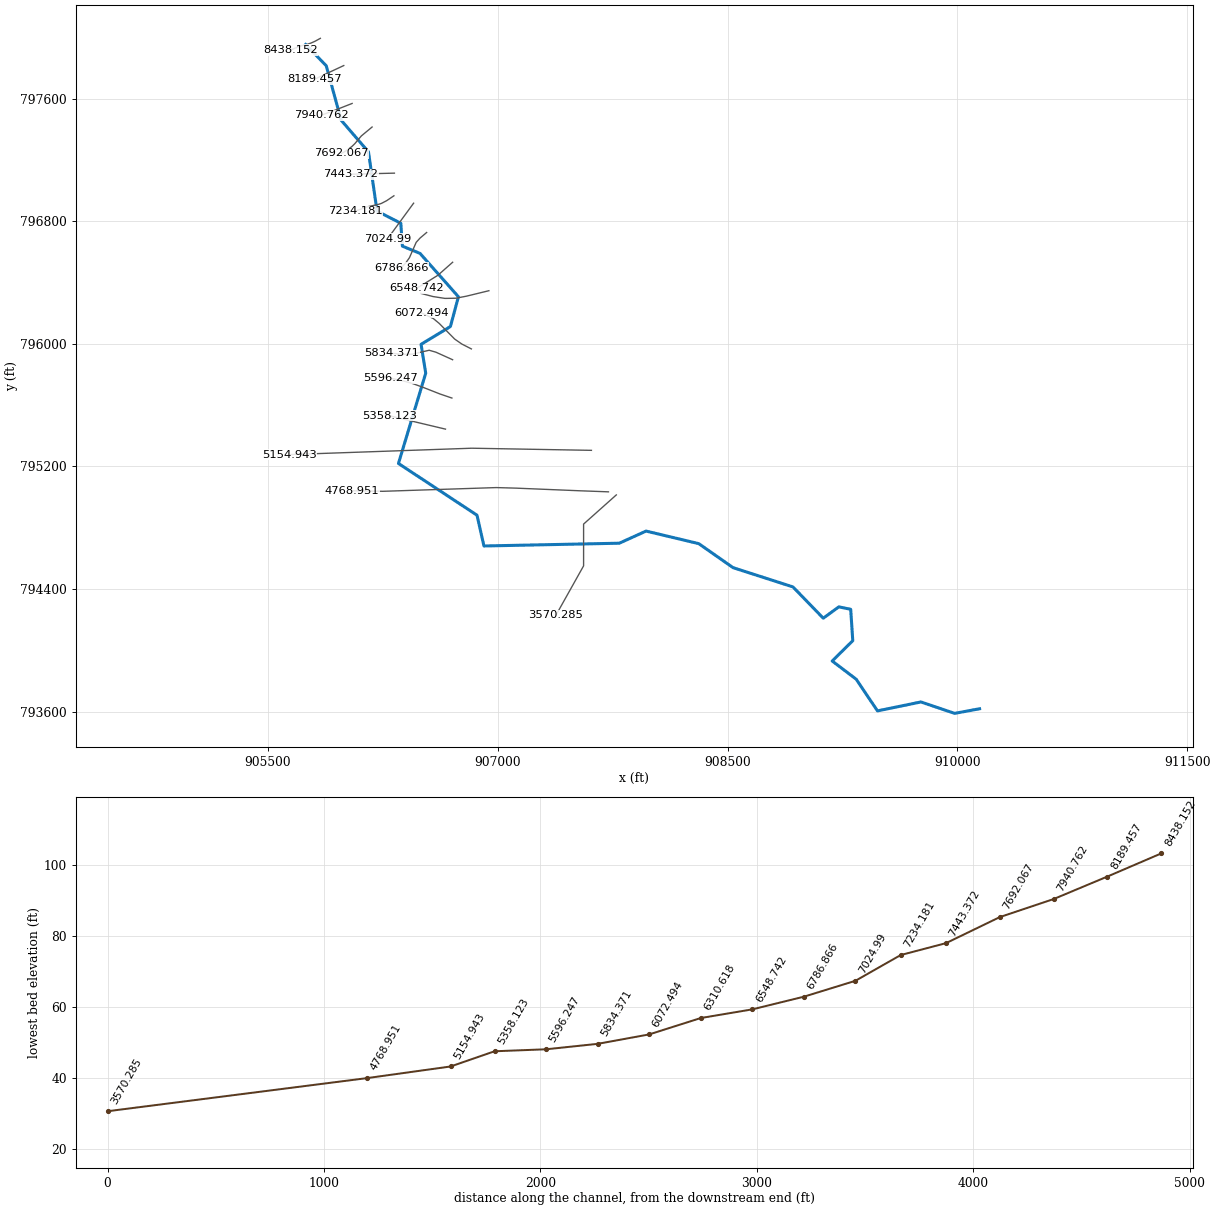
--- 12019_ras.prj (project) ---

Proj Title=12019
Current Plan=p01
Default Exp/Contr=0.3,0.1
English Units
Geom File=g01
Flow File=f01
Plan File=p01
Y Axis Title=Elevation
X Axis Title(PF)=Main Channel Distance
X Axis Title(XS)=Station
BEGIN DESCRIPTION:
RFD model 12019 exported to HEC-RAS
END DESCRIPTION:

--- 12019_ras.p01 (plan) ---

Plan Title=Plan 01
Program Version=4.10
Short Identifier=Plan 01
Geom File=g01
Flow File=f01
Subcritical Flow
Calc Critical at every XS
Secant Critical Depth

--- 12019_ras.f01 (steady flow) ---

Flow Title=Flow 01
Program Version=5.01
Number of Profiles= 6
Profile Names=10yr,25yr,50yr,100yr,100plus,500yr
River Rch & RM=12019,17,8438.152
  223.51  351.33  468.91  573.69  837.59 1373.36
River Rch & RM=12019,17,7940.762
  227.85  358.27   478.3   585.3  854.54 1397.82
River Rch & RM=12019,17,7692.067
  294.49  464.52  621.57  761.91 1112.39  1759.2
River Rch & RM=12019,17,7443.372
  297.46  469.29  628.03  769.89 1124.05 1775.36
River Rch & RM=12019,17,7234.181
  308.17  486.47  651.29  798.68 1166.07 1833.48
River Rch & RM=12019,17, 7024.99
  314.78  497.08  665.65  816.44 1192.01  1869.2
River Rch & RM=12019,17,6786.866
  323.19  510.56  683.92  839.04 1224.99 1914.44
River Rch & RM=12019,17,6548.742
  327.55  517.57  693.41  850.77 1242.13 1937.88
River Rch & RM=12019,17,6310.618
  483.77   767.4 1031.09 1267.68 1850.81  2740.6
River Rch & RM=12019,17,6072.494
  486.68  772.12 1037.53 1275.69  1862.5 2755.89
River Rch & RM=12019,17,5834.371
  494.19  784.26 1054.04 1296.19 1892.44 2794.81
River Rch & RM=12019,17,5596.247
  501.61  796.27 1070.41 1316.55 1922.17 2833.53
River Rch & RM=12019,17,5358.123
  508.67  807.72 1086.02 1335.97 1950.51 2870.36
River Rch & RM=12019,17,5154.943
  510.59  810.83 1090.27 1341.25 1958.23 2880.38
Boundary for River Rch & Prof#=12019,17,1
Up Type= 0
Dn Type= 2
Boundary for River Rch & Prof#=12019,17,2
Up Type= 0
Dn Type= 2
Boundary for River Rch & Prof#=12019,17,2
Up Type= 0
Dn Type= 2
Boundary for River Rch & Prof#=12019,17,2
Up Type= 0
Dn Type= 2
Boundary for River Rch & Prof#=12019,17,2
Up Type= 0
Dn Type= 2
Boundary for River Rch & Prof#=12019,17,2
Up Type= 0
Dn Type= 2

--- 12019_ras.g01 (geometry) ---

Geom Title=12019
Program Version=4.10

River Reach=12019,17
Reach XY= 30
905745.242360295797953.859656821905879.810285483797814.839386035
905977.466535481797458.936608262906155.417924407  797252.7734138
906211.295901806796866.264010257906366.499154272796787.035411692
906376.908109069796637.534479354906492.275706205796589.882769983
906742.612594727796307.054383436906690.182282212796112.715106235
 906498.81608546795996.669637381906529.081152798795808.073710061
906351.093078733795219.090895288906863.911363337794881.278106319
906909.036235008794680.451415792907792.594446423794698.540484865
907967.483896584794777.730011044908311.233896586794695.698761021
908534.929278853 794539.08373813908926.092953325794413.224982791
909123.910021515794208.987585509909225.582078935794283.104617841
909302.990557703794267.114515674909316.462087422794062.265419414
909182.220138343793929.623916362909338.821172596793810.847815206
909477.734713766793604.098434203909761.420158089793662.395804313
909981.331641763793587.870052266910144.166114153793618.016067687

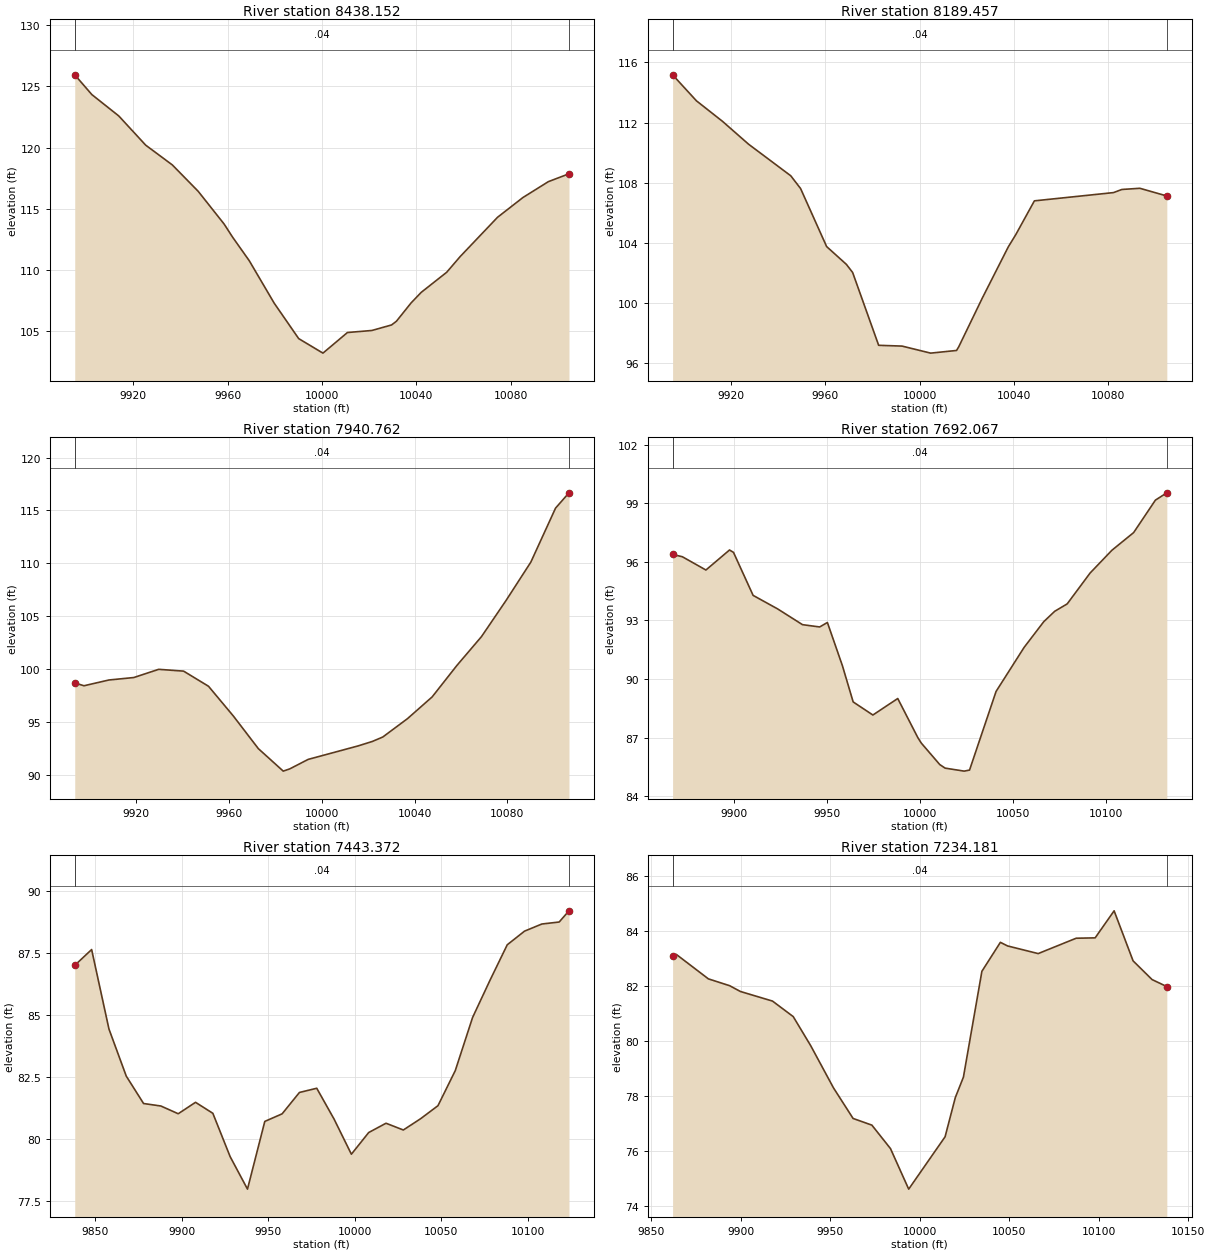
Type RM Length L Ch R = 1 ,8438.152,248.695000,248.695000,248.695000
XS GIS Cut Line= 6
905841.345537064797993.906290672905807.585720552797975.316685657
905781.664705124797963.672349028905761.589185308797956.828254087
905709.026051497797942.774459227905646.895716725 797917.77426942
#Sta/Elev= 24
9895.213125.95399902.457124.33819913.873122.58939925.289120.19939936.587118.5805
 9947.55116.42219958.513113.75179962.169112.6616 9969.21110.73959979.776107.2688
9990.166104.366610000.45103.178710010.83104.864410021.21105.032910029.53 105.483
10031.59 105.785 10037.8107.282910042.14108.155910052.92109.796210058.62111.0784
10074.47114.294610085.25115.913710096.03117.212610104.77117.8549
#Mann= 3 , 0 , 0
9895.213    0.04       09895.213    0.04       010104.77    0.04       0
#XS Ineff= 2 , 0
       0                               0
Bank Sta=9895.213,10104.77
Exp/Cntr=0.3,0.1

Type RM Length L Ch R = 1 ,8189.457,248.695000,248.695000,248.695000
XS GIS Cut Line= 5
905994.169348347797816.224866018905900.137696091797772.258312743
905898.314954892797771.435139298905857.733635944797752.985391601
905804.768369273797726.466869553
#Sta/Elev= 22
9895.197115.17649905.319113.44829916.359112.08689927.398110.56949945.308108.4694
9949.476107.62279960.515 103.7679968.918102.58029971.554102.04449982.59397.20469
9992.527 97.152110004.6496.6848310015.6396.8616510016.5597.1040710026.61100.3611
 10037.6103.752910040.71104.547110048.64106.802610082.19 107.35110085.75107.5592
10093.37107.637210104.81107.1269
#Mann= 3 , 0 , 0
9895.197    0.04       09895.197    0.04       010104.81    0.04       0
#XS Ineff= 2 , 0
       0                               0
Bank Sta=9895.197,10104.81
Exp/Cntr=0.3,0.1

Type RM Length L Ch R = 1 ,7940.762,248.695000,248.695000,248.695000
XS GIS Cut Line= 5
906048.711933083797568.860634377905950.427225099797530.312536035
905948.570271717797529.569754683 905929.20743612797521.982544179
905849.552156398797492.953876692
#Sta/Elev= 23
9893.42698.692659897.41398.424259908.15598.968419918.89799.201819929.63899.97788
 9940.3899.807049951.12298.375069961.86395.552659972.60592.479139983.34690.35162
9986.16290.564679994.08891.4603210015.5792.73175 10021.893.1602310026.2793.57606
10036.9295.3122110047.5697.36804 10058.2100.333610068.85 103.07310079.49106.5051
10090.13110.115610100.78115.219510106.58116.6675
#Mann= 3 , 0 , 0
9893.426    0.04       09893.426    0.04       010106.58    0.04       0
#XS Ineff= 2 , 0
       0                               0
Bank Sta=9893.426,10106.58
Exp/Cntr=0.3,0.1

Type RM Length L Ch R = 1 ,7692.067,248.695000,248.695000,248.695000
XS GIS Cut Line= 6
906179.120712242797415.092365515906108.955868156797356.885449547
 906066.77963009797307.014803036906048.153581221797288.665513349
906018.150430553797265.655596672905979.749743526797242.451708957
#Sta/Elev= 30
9867.27596.383169872.497 96.2677 9885.1795.586829897.84496.611979899.98296.49014
9910.51794.286769923.66693.594839937.03692.786389946.26392.669239950.40692.89782
9958.48790.679899964.24588.827769974.84488.156689988.18789.00253    999986.99454
10000.8186.7220110010.7385.6197710013.6385.4353410023.8785.2819310026.7485.33597
10040.99 89.365510056.0491.6207210066.5992.9380410072.4793.4713610079.1993.85152
 10091.595.4336510103.1996.5985410114.8797.5045810126.5599.1671710132.6999.54178
#Mann= 3 , 0 , 0
9867.275    0.04       09867.275    0.04       010132.69    0.04       0
#XS Ineff= 2 , 0
       0                               0
Bank Sta=9867.275,10132.69
Exp/Cntr=0.3,0.1

Type RM Length L Ch R = 1 ,7443.372,209.191400,209.191400,209.191400
XS GIS Cut Line= 2
906324.748327503797114.000173222906039.341676862797107.039035402
#Sta/Elev= 30
9838.26586.982939848.01787.62045 9858.0284.416649868.02382.516149878.02681.41133
9888.02981.311239898.03280.999459908.03481.460139918.03781.01706 9928.0479.26796
9938.04377.959659948.04680.690349958.04980.995469968.052 81.85719978.05582.02718
9988.05880.784259998.061 79.367510008.0680.2415710018.0780.6164710028.0780.34378
10038.0780.7998410048.0881.3239910058.08 82.739410068.0884.8823110078.0986.37537
10088.0987.8117710098.0988.3628710108.09 88.6499 10118.188.7308510123.7689.18172
#Mann= 3 , 0 , 0
9838.265    0.04       09838.265    0.04       010123.76    0.04       0
#XS Ineff= 2 , 0
       0                               0
Bank Sta=9838.265,10123.76
Exp/Cntr=0.3,0.1

Type RM Length L Ch R = 1 ,7234.181,209.191300,209.191300,209.191300
XS GIS Cut Line= 6
906321.436108229796966.159682529906273.240202689796933.725101499
906239.109399302796916.125550339906218.530210158796909.552598019
906151.603612289796895.160621085906067.237706553796865.444924417
#Sta/Elev= 26
9862.00383.10314 9864.0883.147799881.99182.258459893.86882.010059899.90281.79932
9917.81381.450919929.36780.887469939.13479.83093 9951.8778.296029962.81177.18478
9973.30976.941849983.69576.089839993.87774.61565 10014.276.51868 10019.977.94127
10024.4478.6865510034.7682.5336410045.0983.5864710049.0883.45562 10066.283.17748
10087.4183.7355810098.0183.7489510108.6184.7316810119.2182.9123810129.8282.23234
10138.0581.97779
#Mann= 3 , 0 , 0
9862.003    0.04       09862.003    0.04       010138.05    0.04       0
#XS Ineff= 2 , 0
       0                               0
Bank Sta=9862.003,10138.05
Exp/Cntr=0.3,0.1

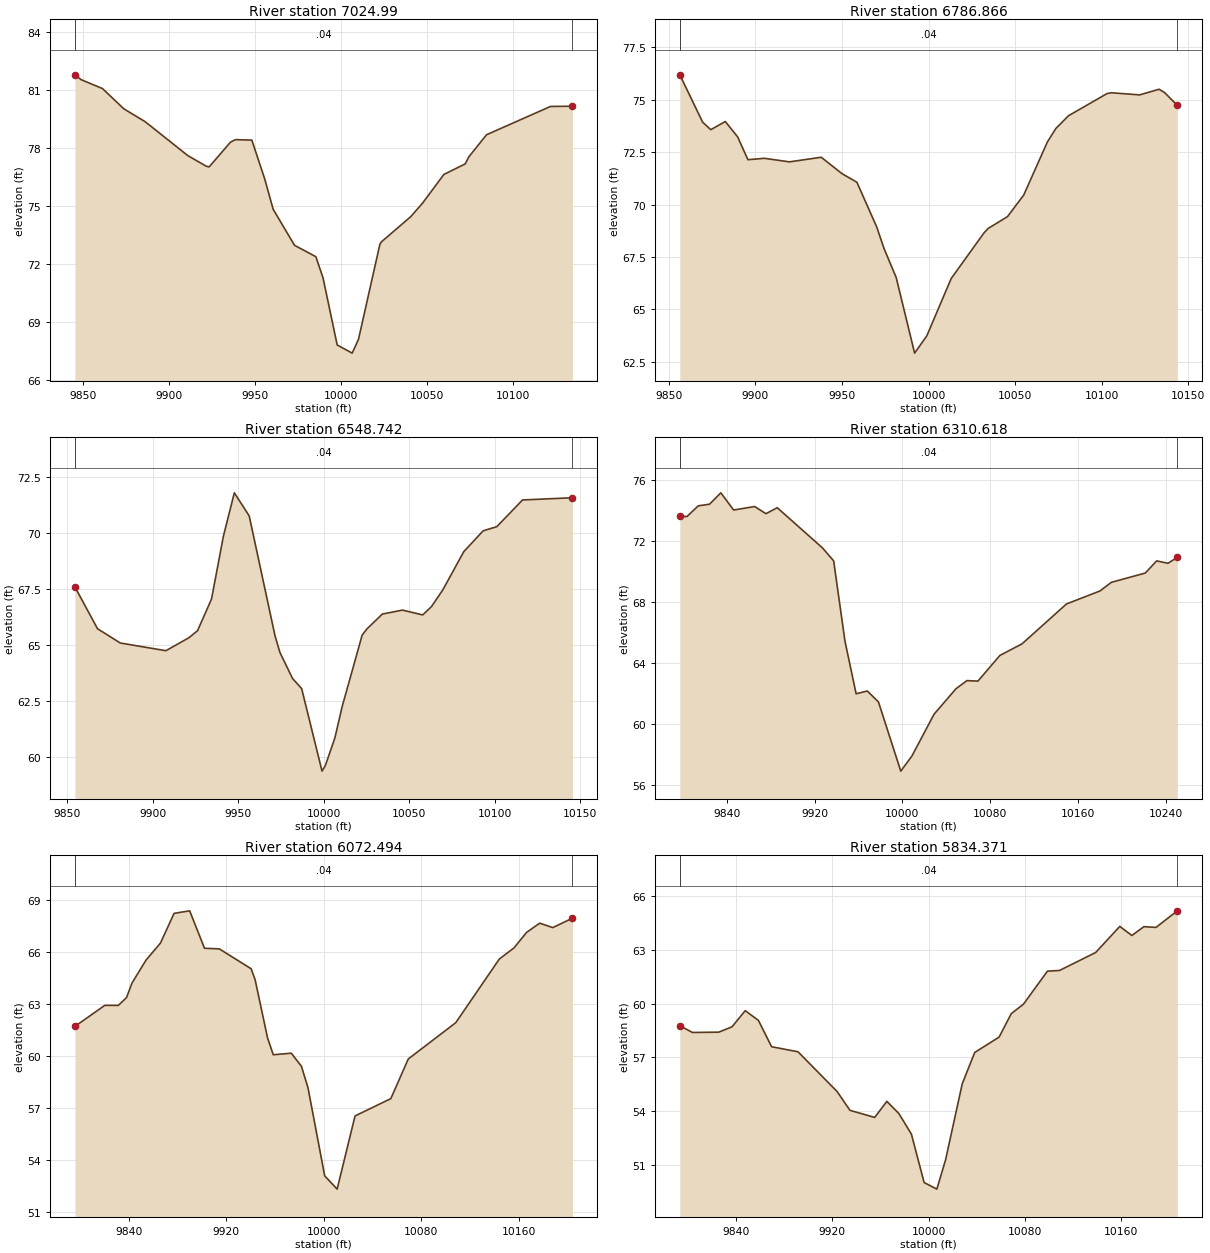
Type RM Length L Ch R = 1 , 7024.99,238.123800,238.123800,238.123800
XS GIS Cut Line= 2
906450.048808272796917.928124611906279.500931669796684.730007624
#Sta/Elev= 29
9845.43581.770889849.06381.519569861.45281.060379873.841 80.0136 9886.2379.34834
9911.00877.594069921.74877.043829923.396 77.01129935.78578.291399938.68878.42047
9948.17478.394269955.62876.395289960.56374.818649972.952 72.95729985.34172.36869
9989.50871.27537 9997.7367.8028610006.4567.3822410010.1268.1017810022.5173.00201
10023.3973.1334810040.3374.4281810047.2975.1350810059.6876.6206110072.0677.16417
10074.2177.5338510084.4578.6723610121.6280.1365610134.3480.14659
#Mann= 3 , 0 , 0
9845.435    0.04       09845.435    0.04       010134.34    0.04       0
#XS Ineff= 2 , 0
       0                               0
Bank Sta=9845.435,10134.34
Exp/Cntr=0.3,0.1

Type RM Length L Ch R = 1 ,6786.866,238.123800,238.123800,238.123800
XS GIS Cut Line= 6
906535.077915428796726.543676011906492.182498797796690.325821421
906466.913517074796662.451654146906422.789766857796562.031068182
906397.975904269796526.832681235906369.988872105796497.362846735
#Sta/Elev= 30
9856.26876.194849869.45873.936139874.162  73.5779882.54673.966369889.66373.23802
9895.63372.144199905.16372.211489919.59772.040989937.99272.261229950.03271.47597
9958.59371.069559970.08368.927999974.22467.915689981.319  66.5199991.94262.91416
    999963.7404410013.0966.4749410032.1268.6607310034.5168.8673510045.6369.42923
10054.99 70.456910068.6572.9867810073.5773.6345910080.8974.2437410103.1275.29909
10105.6475.3389710121.9675.2375410133.2375.5070810136.4875.3427810143.7674.73509
#Mann= 3 , 0 , 0
9856.268    0.04       09856.268    0.04       010143.76    0.04       0
#XS Ineff= 2 , 0
       0                               0
Bank Sta=9856.268,10143.76
Exp/Cntr=0.3,0.1

Type RM Length L Ch R = 1 ,6548.742,238.123800,238.123800,238.123800
XS GIS Cut Line= 6
 906704.89920295796532.478862224906609.465364703796448.206319554
  906595.0418563796438.874456255906593.266134032796437.954233222
906513.307517316796387.919601197906469.561334217796363.282621485
#Sta/Elev= 30
9854.50467.580079867.71165.715149881.05265.077159907.73364.733669921.07465.30716
9926.23465.625589934.41567.038969941.34269.836689947.75671.77832 9956.4570.74931
9971.55765.396389974.43764.652919981.82163.492329987.13963.041769999.04759.36023
   10001 59.610510006.5760.8405710010.7562.2174710022.5565.4355810025.4265.71497
10034.3466.3689310046.1466.5451310057.9466.3300410063.12 66.705810069.7367.45056
10081.9869.1550710093.3370.0849510101.2770.2667410116.3371.4598810145.5371.55867
#Mann= 3 , 0 , 0
9854.504    0.04       09854.504    0.04       010145.53    0.04       0
#XS Ineff= 2 , 0
       0                               0
Bank Sta=9854.504,10145.53
Exp/Cntr=0.3,0.1

Type RM Length L Ch R = 1 ,6310.618,238.123800,238.123800,238.123800
XS GIS Cut Line= 6
906941.353017135796346.589773347906794.717647085796310.958177111
 906725.67003983796297.641032796906654.736820455796296.416162071
906576.611820455796308.568939849906496.750709344796329.402273182
#Sta/Elev= 30
 9796.9573.599429803.48873.590059813.779 74.2884 9824.0774.395399834.36175.14009
9846.03474.014029865.23474.242899875.52573.774219885.81674.16696 9926.9871.53952
9937.27170.684929947.562 65.43799957.74961.984589967.93362.166199978.11761.45293
9998.48556.9196910008.6657.9102410028.8560.6481810048.8562.3162510058.8562.84476
10068.8562.8130310088.8664.4925410109.0965.2536210149.5767.8618310180.18 68.7156
10190.5269.2794710221.5269.8890410231.8670.6845110242.1970.5267510250.7270.91481
#Mann= 3 , 0 , 0
 9796.95    0.04       0 9796.95    0.04       010250.72    0.04       0
#XS Ineff= 2 , 0
       0                               0
Bank Sta=9796.95,10250.72
Exp/Cntr=0.3,0.1

Type RM Length L Ch R = 1 ,6072.494,238.123800,238.123800,238.123800
XS GIS Cut Line= 6
906827.108433578795966.696290204906764.662570648795998.642005824
906718.140217739796030.924860295906617.381335624796132.934059868
906578.650878137796165.038670666906500.009484655796202.620508479
#Sta/Elev= 30
9795.94561.703319820.461 62.91949831.55162.916219838.29363.36986 9842.77 64.2079
9854.25465.526589866.12566.513259877.277  68.2239890.05868.369859902.22966.21149
9914.40166.174929940.46665.028869943.73764.398689953.94861.039839958.64860.06899
9973.38660.160679981.70559.407439987.10458.16775 10000.853.08789   1001152.32134
10025.6956.5411210055.0657.5413710069.34 59.826410108.3161.9205510144.05 65.5927
10156.0466.2306610166.3767.1249210177.1267.6590210187.8767.4033610203.9967.94391
#Mann= 3 , 0 , 0
9795.945    0.04       09795.945    0.04       010203.99    0.04       0
#XS Ineff= 2 , 0
       0                               0
Bank Sta=9795.945,10203.99
Exp/Cntr=0.3,0.1

Type RM Length L Ch R = 1 ,5834.371,238.123800,238.123800,238.123800
XS GIS Cut Line= 6
906704.546775534795896.176683882906595.928823242 795945.20529415
 906551.73670277795958.005398073906441.339715685795932.345106887
906391.760983395795931.315573462 906307.31611161795937.768374027
#Sta/Elev= 30
9793.26858.767349803.74258.390559825.68558.407799836.65758.706849847.62859.60477
  9858.6 59.06269869.57157.596919891.51457.315279924.04455.098499934.66354.05708
9955.24853.659949965.32854.555739975.35753.875669985.75352.729629996.29750.03755
10006.89 49.668610014.1551.29894   1002855.5319110038.3657.2766510058.6458.13316
10068.7859.4422210078.8359.9617710098.83 61.805310108.8361.8420910138.8962.84197
10158.9464.2958810168.97   63.79   1017964.2806310189.0364.2408410206.7765.16282
#Mann= 3 , 0 , 0
9793.268    0.04       09793.268    0.04       010206.77    0.04       0
#XS Ineff= 2 , 0
       0                               0
Bank Sta=9793.268,10206.77
Exp/Cntr=0.3,0.1

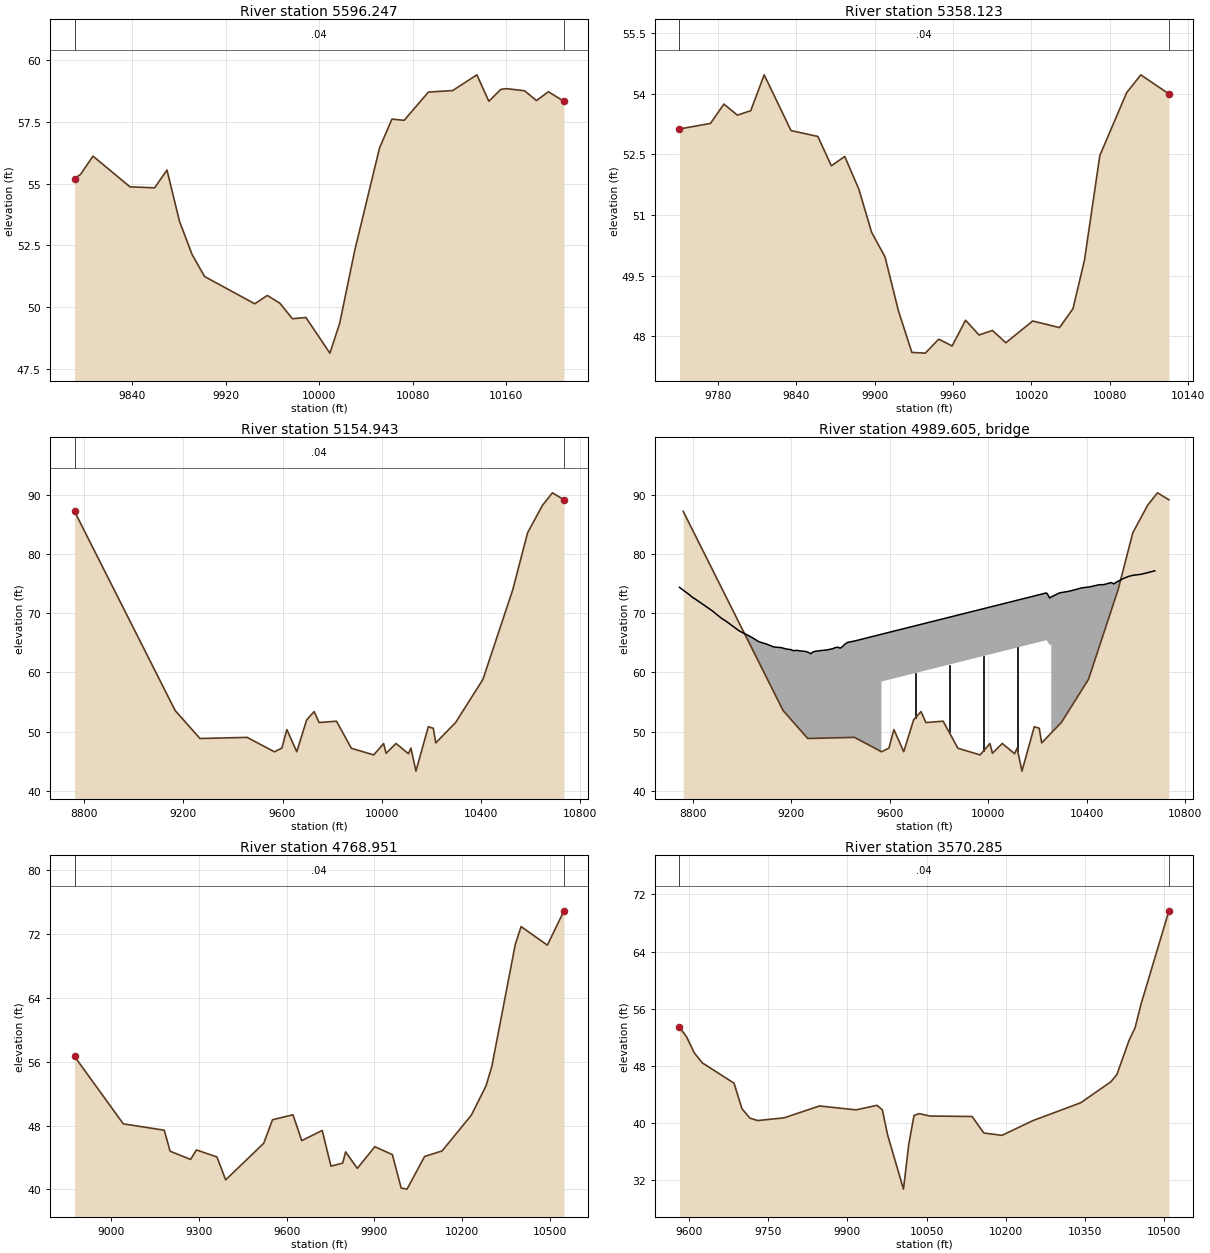
Type RM Length L Ch R = 1 ,5596.247,238.123800,238.123800,238.123800
XS GIS Cut Line= 6
906699.963489052795646.108925728906622.902239964795672.301581838
906510.138014422795716.623033968906441.192264964795741.469428654
906372.421386068795760.571487531906301.892200992795774.629520631
#Sta/Elev= 30
9790.42355.203129795.66655.381139806.22856.116959837.913 54.87479859.03754.83375
9869.59955.553369880.30553.48118 9891.0552.138619901.79451.242549944.77350.13804
9955.51850.476929966.26350.162159977.00749.534079988.53949.58336 10009.148.14082
10017.48 49.349210030.3552.2939810051.5956.4473410062.2257.6158910072.6957.56596
10093.4558.71054 10114.258.7710610134.9659.40837 10145.258.33722 10155.458.81864
10160.2958.8485310175.7958.7632310185.9958.3666410196.1958.7247610209.5558.33314
#Mann= 3 , 0 , 0
9790.423    0.04       09790.423    0.04       010209.55    0.04       0
#XS Ineff= 2 , 0
       0                               0
Bank Sta=9790.423,10209.55
Exp/Cntr=0.3,0.1

Type RM Length L Ch R = 1 ,5358.123,203.180300,203.180300,203.180300
XS GIS Cut Line= 2
906658.115047588795443.176855914906293.531714255 795529.98241147
#Sta/Elev= 30
9750.46153.127839774.222  53.2659784.502 53.74399794.781 53.46949805.06153.57916
 9815.3454.466929835.89953.087449856.45952.942949866.73852.216989877.01852.44745
9887.85451.635099897.57750.573389907.85649.964279918.13648.629159928.41547.60102
9938.69547.583399948.97447.928629959.254 47.76089969.53348.397179979.81348.03238
9990.09348.1448810000.3747.8399310020.9348.3780710041.4948.2150310051.77 48.6823
10060.5549.8775910072.3352.4701910092.8954.0275110103.7254.4656910125.2453.99491
#Mann= 3 , 0 , 0
9750.461    0.04       09750.461    0.04       010125.24    0.04       0
#XS Ineff= 2 , 0
       0                               0
Bank Sta=9750.461,10125.24
Exp/Cntr=0.3,0.1

Type RM Length L Ch R = 1 ,5154.943,385.991500,385.991500,385.991500
XS GIS Cut Line= 3
907610.659343361 795304.70753018906829.409343361795318.596419069
905638.437121139795276.929752402
#Sta/Elev= 30
8761.62687.253039167.349 53.55479267.36548.826139457.39549.016459567.42446.57755
9597.44247.205899617.45450.338399657.47946.585479697.50351.975779727.52153.37781
9747.53451.527219817.577 51.75429877.61347.173569967.66846.0525610007.6947.97307
 10017.746.3248610057.7247.9874410107.7546.2480510117.7647.2065110137.7743.30787
 10187.850.8210110207.8250.5552410217.8248.0884810297.8751.5349810407.9458.82914
10528.0173.9657810588.0583.6331410648.0888.2762310688.1190.38151 10734.789.20001
#Mann= 3 , 0 , 0
8761.626    0.04       08761.626    0.04       0 10734.7    0.04       0
#XS Ineff= 2 , 0
       09527.881                       0
Bank Sta=8761.626,10734.7
Exp/Cntr=0.3,0.1

Type RM Length L Ch R = 3 ,4989.605,,,
BEGIN DESCRIPTION:
END DESCRIPTION:
Bridge Culvert--1,0,-1,-1, 0
Deck Dist Width WeirC Skew NumUp NumDn MinLoCord MaxHiCord MaxSubmerge Is_Ogee
136.495750,113.000000,2.6,0, 52, 53, , , 0.95, 0, 0,0,,
 8746.39 8789.43 8799.44 8809.44 8879.48 8919.50 8929.51 8989.54 9039.57 9069.59
 9099.60 9129.62 9159.64 9179.65 9199.66 9209.66 9219.67 9259.69 9269.70 9279.70
 9289.71 9299.71 9349.74 9369.75 9379.76 9389.77 9399.77 9409.78 9419.78 9429.79
 9458.97 9566.80 9566.8010235.6810240.3710250.3810256.8010256.8010290.4110330.44
10380.4810410.5010450.5310470.5410500.5610510.5710520.5810550.6010570.6110590.63
10620.6510677.36
   74.40   73.06   72.68   72.45   70.43   69.07   68.85   67.02   65.96   65.19
   64.81   64.31   64.20   63.97   63.85   63.68   63.74   63.54   63.41   63.16
   63.49   63.59   63.84   64.03   64.21   64.26   64.11   64.42   64.83   65.09
   65.33   66.46   66.46   73.44   73.33   72.59   72.79   72.79   73.46   73.74
   74.31   74.46   74.83   74.86   75.21   74.97   75.26   75.91   76.24   76.45
   76.59   77.19
 -925.60 -926.94 -927.32 -927.55 -929.57 -930.93 -931.15 -932.98 -934.04 -934.81
 -935.19 -935.69 -935.80 -936.03 -936.15 -936.32 -936.26 -936.46 -936.59 -936.84
 -936.51 -936.41 -936.16 -935.97 -935.79 -935.74 -935.89 -935.58 -935.17 -934.91
 -934.67 -933.54   58.46   65.44   65.33   64.59   64.79 -927.21 -926.54 -926.26
 -925.69 -925.54 -925.17 -925.14 -924.79 -925.03 -924.74 -924.09 -923.76 -923.55
 -923.41 -922.81
 8746.39 8789.43 8799.44 8809.44 8879.48 8919.50 8929.51 8989.54 9039.57 9069.59
 9099.60 9129.62 9159.64 9179.65 9199.66 9209.66 9219.67 9259.69 9269.70 9279.70
 9289.71 9299.71 9349.74 9369.75 9379.76 9389.77 9399.77 9409.78 9419.78 9429.79
 9458.97 9554.11 9554.1110235.6810240.3710244.1110244.1110250.3810260.3910290.41
10330.4410380.4810410.5010450.5310470.5410500.5610510.5710520.5810550.6010570.61
10590.6310620.6510677.36
   74.40   73.06   72.68   72.45   70.43   69.07   68.85   67.02   65.96   65.19
   64.81   64.31   64.20   63.97   63.85   63.68   63.74   63.54   63.41   63.16
   63.49   63.59   63.84   64.03   64.21   64.26   64.11   64.42   64.83   65.09
   65.33   66.33   66.33   73.44   73.33   73.05   73.05   72.59   72.90   73.46
   73.74   74.31   74.46   74.83   74.86   75.21   74.97   75.26   75.91   76.24
   76.45   76.59   77.19
 -925.60 -926.94 -927.32 -927.55 -929.57 -930.93 -931.15 -932.98 -934.04 -934.81
 -935.19 -935.69 -935.80 -936.03 -936.15 -936.32 -936.26 -936.46 -936.59 -936.84
 -936.51 -936.41 -936.16 -935.97 -935.79 -935.74 -935.89 -935.58 -935.17 -934.91
 -934.67 -933.67   58.33   65.44   65.33   65.05 -926.95 -927.41 -927.10 -926.54
 -926.26 -925.69 -925.54 -925.17 -925.14 -924.79 -925.03 -924.74 -924.09 -923.76
 -923.55 -923.41 -922.81
Pier Skew, UpSta & Num, DnSta & Num=  ,9703.60, 2 ,9690.91, 2 , 0 , 0 , 0 ,,
    4.00    4.00
 -932.11   67.89
    4.00    4.00
 -932.25   67.75
Pier Skew, UpSta & Num, DnSta & Num=  ,9842.40, 2 ,9829.71, 2 , 0 , 0 , 0 ,,
    4.00    4.00
 -930.67   69.33
    4.00    4.00
 -930.80   69.20
Pier Skew, UpSta & Num, DnSta & Num=  ,9981.20, 2 ,9968.51, 2 , 0 , 0 , 0 ,,
    4.00    4.00
 -929.22   70.78
    4.00    4.00
 -929.35   70.65
Pier Skew, UpSta & Num, DnSta & Num=  ,10120.00, 2 ,10107.31, 2 , 0 , 0 , 0 ,,
    4.00    4.00
 -927.77   72.23
    4.00    4.00
 -927.90   72.10
BR Coef=-1 , 0 , 0 ,, 0 ,,,0.8,0,1,0,
WSPro=,,,, 1 ,,,, 0 ,,,, 0 ,,,,-1 ,-1 ,-1 , 0 , 0 , 0 , 0 , 0
BC Design=,, 0 ,, 0 ,,,,,,

Type RM Length L Ch R = 1 ,4768.951,1198.666300,1198.666300,1198.666300
XS GIS Cut Line= 6
907721.770454472795033.874196846907534.270454472795040.818641291
907114.131565583795058.179752402906989.131565583795061.651974624
 906249.54823225795037.346419069906048.159343361795040.818641291
#Sta/Elev= 30
8874.44256.655039041.32748.212139181.443  47.412 9201.4644.78672 9271.52 43.7596
9291.53744.946289361.59644.070029391.62241.201649521.71545.776989551.72648.72386
9621.75549.350869651.77246.115849721.80947.382429751.82642.912429791.84743.30316
9801.85344.702129841.874 42.63929901.90745.351829961.93944.357979991.955 40.1714
10011.9740.04079   1007244.1222810132.0344.8253510232.0849.3022710282.1152.95414
10302.1255.3935110382.1570.6374510402.1672.9002910492.17 70.577210549.02 74.8733
#Mann= 3 , 0 , 0
8874.442    0.04       08874.442    0.04       010549.02    0.04       0
#XS Ineff= 2 , 0
       09559.484                       0
Bank Sta=8874.442,10549.02
Exp/Cntr=0.3,0.1

Type RM Length L Ch R = 1 ,3570.285,0.000000,0.000000,0.000000
XS GIS Cut Line= 4
907773.104932124 795013.81496152907559.519792562794823.389656369
907559.519792562794550.618273314907379.387747149794228.953906503
#Sta/Elev= 30
9581.74653.414349594.99252.086439610.01949.796429625.04548.412669685.15245.57523
9700.17941.998539715.20640.672119730.233 40.33399780.16740.720289847.15442.37748
9916.28341.833019956.283 42.46919966.28341.829929976.283 38.304510006.28 30.7354
10016.2836.9856510026.2841.0589710036.2841.3022410056.2840.9719710136.2840.90211
10158.5738.5903910192.9538.2652710252.2540.3479110341.9542.8214710399.2545.76084
10410.71 46.774110433.6451.53543 10445.153.3177310456.9156.7531410509.3369.69789
#Mann= 3 , 0 , 0
9581.746    0.04       09581.746    0.04       010509.33    0.04       0
#XS Ineff= 2 , 0
       09874.752                       0
Bank Sta=9581.746,10509.33
Exp/Cntr=0.3,0.1